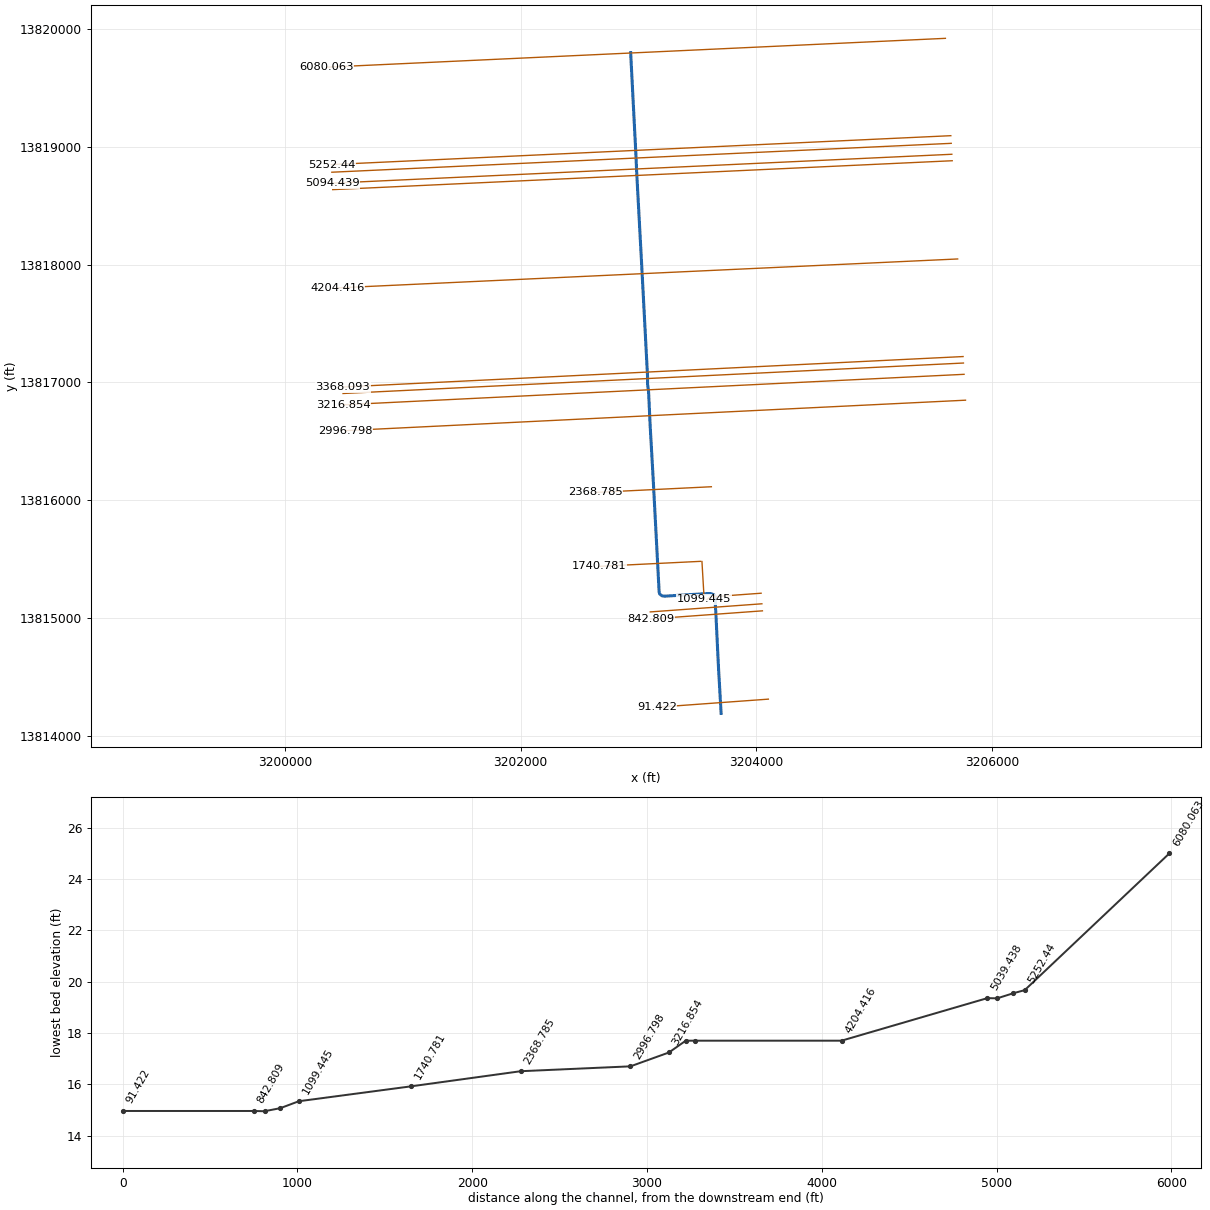
--- B112_04_00.prj (project) ---

Proj Title=B112-04-00
Current Plan=p02
Default Exp/Contr=.3,.1
English Units
Geom File=g02
Geom File=g03
Flow File=f03
Flow File=f04
Plan File=p02
Plan File=p03
Y Axis Title=Elevation
X Axis Title(PF)=Main Channel Distance
X Axis Title(XS)=Station
BEGIN DESCRIPTION:
Armand Bayou
Willow Springs Bayou Trib B
HCFCD Unit B112-04-00
Flood Hazard Model
10, 2, 1, 0.2% Event
Filename B112_04_00.prj
Prepared by: Christopher Moss Date: 6/15/2004
Reviewd by:		Date:
Status FINAL
END DESCRIPTION:
DSS Export Rating Curves= 0
DSS Export Rating Curve Sorted= 0
DSS Export Volume Flow Curves= 0
DXF OffsetX= 0
DXF OffsetY= 0
DXF ScaleX= 1
DXF ScaleY= 10

--- B112_04_00.p02 (plan) ---

Plan Title=FEMA Effective June 2007
Version=Version 3.0.1  Mar 2001
Short Identifier=FEMAeff0607
Geom File=g02
Flow File=f03
Subcritical Flow
K Sum by GR= 0
Std Step Tol= 0.01
Critical Tol= 0.01
Num of Std Step Trials= 20
Max Error Tol= 0.3
Flow Tol Ratio= 0.001
Split Flow NTrial= 30
Split Flow Tol= 0.02
Split Flow Ratio= 0.02
Log Output Level= 0
Friction Slope Method= 0
Unsteady Friction Slope Method= 2
Secant Critical Depth
Global Vel Dist= 0 , 0 , 0
Global Log Level= 0
CheckData=True
Encroach Param=-1 ,0,0, 0
Computation Interval=1HOUR
Output Interval=1HOUR
Run HTab= 0
Run UNet= 0
Run PostProcess= 0
UNET Theta= 1
UNET ZTol= 0.02
UNET ZSATol= 0.05
UNET MxIter= 20
UNET MaxInSteps= 1
UNET DtIC= 0
UNET DtMin= 0
UNET MaxCRTS= 20
UNET WFStab= 2
UNET SFStab= 1
UNET WFX= 1
UNET SFX= 1
UNET Convert EG Bridges=-1
UNET Use Existing IB Tables=-1
Instantaneous Interval=1HOUR
DSS File=dss
Write IC File= 0
IC Time=0
Write Velocity= 0
Write Detailed= 0

--- B112_04_00.p03 (plan) ---

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Plan Title=Floodway
Short Identifier=Floodway0607
Geom File=g03
Flow File=f04
Encroach Param=-1 ,0,0, 2
Encroach River=B112-04-00
Encroach Reach=MAIN
Encroach Node=6080.063
       1 7130.06 7251.87
Encroach Node=5252.44
       1 2636.64 2741.75
Encroach Node=5187.44
       1 2633.55 2748.53
Encroach Node=5140.94
       1 2633.55 2748.53
Encroach Node=5094.439
       1 2633.55 2748.53
Encroach Node=5039.438
       1 2649.66 2744.86
Encroach Node=4204.416
       1 2648.68 2739.89
Encroach Node=3368.093
       1 2626.57 2748.71
Encroach Node=3313.077
       1 2628.72  2784.5
Encroach Node=3265.97
       1 2628.72  2784.5
Encroach Node=3216.854
       1 2628.72  2784.5
Encroach Node=2996.798
       1  2641.7 2755.78
Encroach Node=2368.785
       1  4958.9 5034.32
Encroach Node=1740.781
       1 4976.05 5023.95
Encroach Node=1099.445
       1 4980.05 5027.95
Encroach Node=993.321
       1  4963.2 5056.33
Encroach Node=948.07
       1  4963.2 5056.33
Encroach Node=902.819
       1  4963.2 5056.33
Encroach Node=842.809
       1  4968.2 5061.38
Encroach Node=91.422
       1  4975.3 5039.75
Encroach Reach=B112-04-00_0001
Encroach Node=6080.063
       1 7130.06 7251.87
Encroach Node=5252.44
       1 2636.64 2741.75
Encroach Node=5187.44
       1 2633.55 2748.53
Encroach Node=5140.94
       1 2633.55 2748.53
Encroach Node=5094.439
       1 2633.55 2748.53
Encroach Node=5039.438
       1 2649.66 2744.86
Encroach Node=4204.416
       1 2648.68 2739.89
Encroach Node=3368.093
       1 2626.57 2748.71
Encroach Node=3313.077
       1 2628.72  2784.5
Encroach Node=3265.97
       1 2628.72  2784.5
Encroach Node=3216.854
       1 2628.72  2784.5
Encroach Node=2996.798
       1  2641.7 2755.78
Encroach Node=2368.785
       1  4958.9 5034.32
Encroach Node=1740.781
       1 4976.05 5023.95
Encroach Node=1099.445
       1 4980.05 5027.95
Encroach Node=993.321
       1  4963.2 5056.33
Encroach Node=948.07
       1  4963.2 5056.33
Encroach Node=902.819
       1  4963.2 5056.33
Encroach Node=842.809
       1  4968.2 5061.38
Encroach Node=91.422
       1  4975.3 5039.75

--- B112_04_00.f03 (steady flow) ---

Flow Title=FEMA Effective June 2007
Version=Version 3.0.1  Mar 2001
Number of Profiles= 4
Profile Names=10PCT_10yr, 2PCT_50yr, 1PCT_100yr, 0.2PCT_500yr
River Rch & RM=WS_Trib_B,B112-04-00      ,6080.063
      35      50      59      82
River Rch & RM=WS_Trib_B,B112-04-00      ,5252.44
      36      52      61      85
River Rch & RM=WS_Trib_B,B112-04-00      ,5187.44
      38      55      64      89
River Rch & RM=WS_Trib_B,B112-04-00      ,5094.439
      39      57      66      92
River Rch & RM=WS_Trib_B,B112-04-00      ,5039.438
      61      89     104     145
River Rch & RM=WS_Trib_B,B112-04-00      ,4204.416
      97     141     164     229
River Rch & RM=WS_Trib_B,B112-04-00      ,3368.093
     100     145     169     236
River Rch & RM=WS_Trib_B,B112-04-00      ,3313.077
     105     153     178     249
River Rch & RM=WS_Trib_B,B112-04-00      ,3216.854
     119     172     200     281
River Rch & RM=WS_Trib_B,B112-04-00      ,2996.798
     167     243     282     395
River Rch & RM=WS_Trib_B,B112-04-00      ,2368.785
     236     342     398     557
River Rch & RM=WS_Trib_B,B112-04-00      ,1740.781
     334     485     564     790
River Rch & RM=WS_Trib_B,B112-04-00      ,1099.445
     354     514     598     837
River Rch & RM=WS_Trib_B,B112-04-00      ,993.321
     372     540     628     879
River Rch & RM=WS_Trib_B,B112-04-00      ,902.819
     384     558     649     908
River Rch & RM=WS_Trib_B,B112-04-00      ,842.809
     579     840     977    1368
River Rch & RM=B112-04-00,B112-04-00_0001            ,6080.063
      35      50      59      82
River Rch & RM=B112-04-00,B112-04-00_0001            ,5252.44
      36      52      61      85
River Rch & RM=B112-04-00,B112-04-00_0001            ,5187.44
      38      55      64      89
River Rch & RM=B112-04-00,B112-04-00_0001            ,5094.439
      39      57      66      92
River Rch & RM=B112-04-00,B112-04-00_0001            ,5039.438
      61      89     104     145
River Rch & RM=B112-04-00,B112-04-00_0001            ,4204.416
      97     141     164     229
River Rch & RM=B112-04-00,B112-04-00_0001            ,3368.093
     100     145     169     236
River Rch & RM=B112-04-00,B112-04-00_0001            ,3313.077
     105     153     178     249
River Rch & RM=B112-04-00,B112-04-00_0001            ,3216.854
     119     172     200     281
River Rch & RM=B112-04-00,B112-04-00_0001            ,2996.798
     167     243     282     395
River Rch & RM=B112-04-00,B112-04-00_0001            ,2368.785
     236     342     398     557
River Rch & RM=B112-04-00,B112-04-00_0001            ,1740.781
     334     485     564     790
River Rch & RM=B112-04-00,B112-04-00_0001            ,1099.445
     354     514     598     837
River Rch & RM=B112-04-00,B112-04-00_0001            ,993.321
     372     540     628     879
River Rch & RM=B112-04-00,B112-04-00_0001            ,902.819
     384     558     649     908
River Rch & RM=B112-04-00,B112-04-00_0001            ,842.809
     579     840     977    1368
Boundary for River Rch & Prof#=B112-04-00,B112-04-00_0001            , 1
Up Type= 0
Dn Type= 3
Dn Slope=.001
Boundary for River Rch & Prof#=B112-04-00,B112-04-00_0001            , 2
Up Type= 0
Dn Type= 3
Dn Slope=.001
Boundary for River Rch & Prof#=B112-04-00,B112-04-00_0001            , 3
Up Type= 0
Dn Type= 3
Dn Slope=.001
Boundary for River Rch & Prof#=B112-04-00,B112-04-00_0001            , 4
Up Type= 0
Dn Type= 3
Dn Slope=.001
DSS Import GetInterval= 0
DSS Import GetPeak= 0
DSS Import FillOption= 0

--- B112_04_00.f04 (steady flow) ---

Flow Title=Floodway
Version=Version 3.0.1  Mar 2001
Number of Profiles= 2
Profile Names=1PCT_100yr, 1PCTFloodway_100yrFW
River Rch & RM=B112-04-00,B112-04-00_0001            ,6080.063
      59      59
River Rch & RM=B112-04-00,B112-04-00_0001            ,5252.44
      61      61
River Rch & RM=B112-04-00,B112-04-00_0001            ,5187.44
      64      64
River Rch & RM=B112-04-00,B112-04-00_0001            ,5094.439
      66      66
River Rch & RM=B112-04-00,B112-04-00_0001            ,5039.438
     104     104
River Rch & RM=B112-04-00,B112-04-00_0001            ,4204.416
     164     164
River Rch & RM=B112-04-00,B112-04-00_0001            ,3368.093
     169     169
River Rch & RM=B112-04-00,B112-04-00_0001            ,3313.077
     178     178
River Rch & RM=B112-04-00,B112-04-00_0001            ,3216.854
     200     200
River Rch & RM=B112-04-00,B112-04-00_0001            ,2996.798
     282     282
River Rch & RM=B112-04-00,B112-04-00_0001            ,2368.785
     398     398
River Rch & RM=B112-04-00,B112-04-00_0001            ,1740.781
     564     564
River Rch & RM=B112-04-00,B112-04-00_0001            ,1099.445
     598     598
River Rch & RM=B112-04-00,B112-04-00_0001            ,993.321
     628     628
River Rch & RM=B112-04-00,B112-04-00_0001            ,902.819
     649     649
River Rch & RM=B112-04-00,B112-04-00_0001            ,842.809
     977     977
Boundary for River Rch & Prof#=B112-04-00,B112-04-00_0001            , 1
Up Type= 0
Dn Type= 3
Dn Slope=.001
Boundary for River Rch & Prof#=B112-04-00,B112-04-00_0001            , 2
Up Type= 0
Dn Type= 1
Dn Known WS=22.67
DSS Import GetInterval= 0
DSS Import GetPeak= 0
DSS Import FillOption= 0

--- B112_04_00.g02 (geometry) ---

Geom Title=B112-04-00 June 2007
Version=Version 3.0.1  Mar 2001

River Reach=B112-04-00      ,B112-04-00_0001
Reach XY= 30
       3202933.5       13819800.       3202978.5       13818928.
       3202984.5       13818788.      3203013.68      13818247.5
     3203014.319    13818235.681     3203014.644    13818229.644
     3203016.031    13818203.969     3203019.254    13818144.254
      3203021.56     13818101.56     3203027.447      13817992.5
     3203028.475    13817973.475      3203077.25       13817044.
        3203077.       13816988.      3203085.75       13816920.
      3203099.25       13816631.       3203125.5       13816167.
       3203175.5       13815218.      3203182.75       13815201.
      3203201.75       13815188.      3203225.25       13815186.
        3203584.       13815208.        3203619.       13815207.
       3203642.5       13815196.      3203650.75       13815184.
       3203654.5       13815166.      3203653.75       13815143.
       3203652.5       13815099.        3203656.       13815058.
      3203678.75       13814588.       3203701.5       13814191.

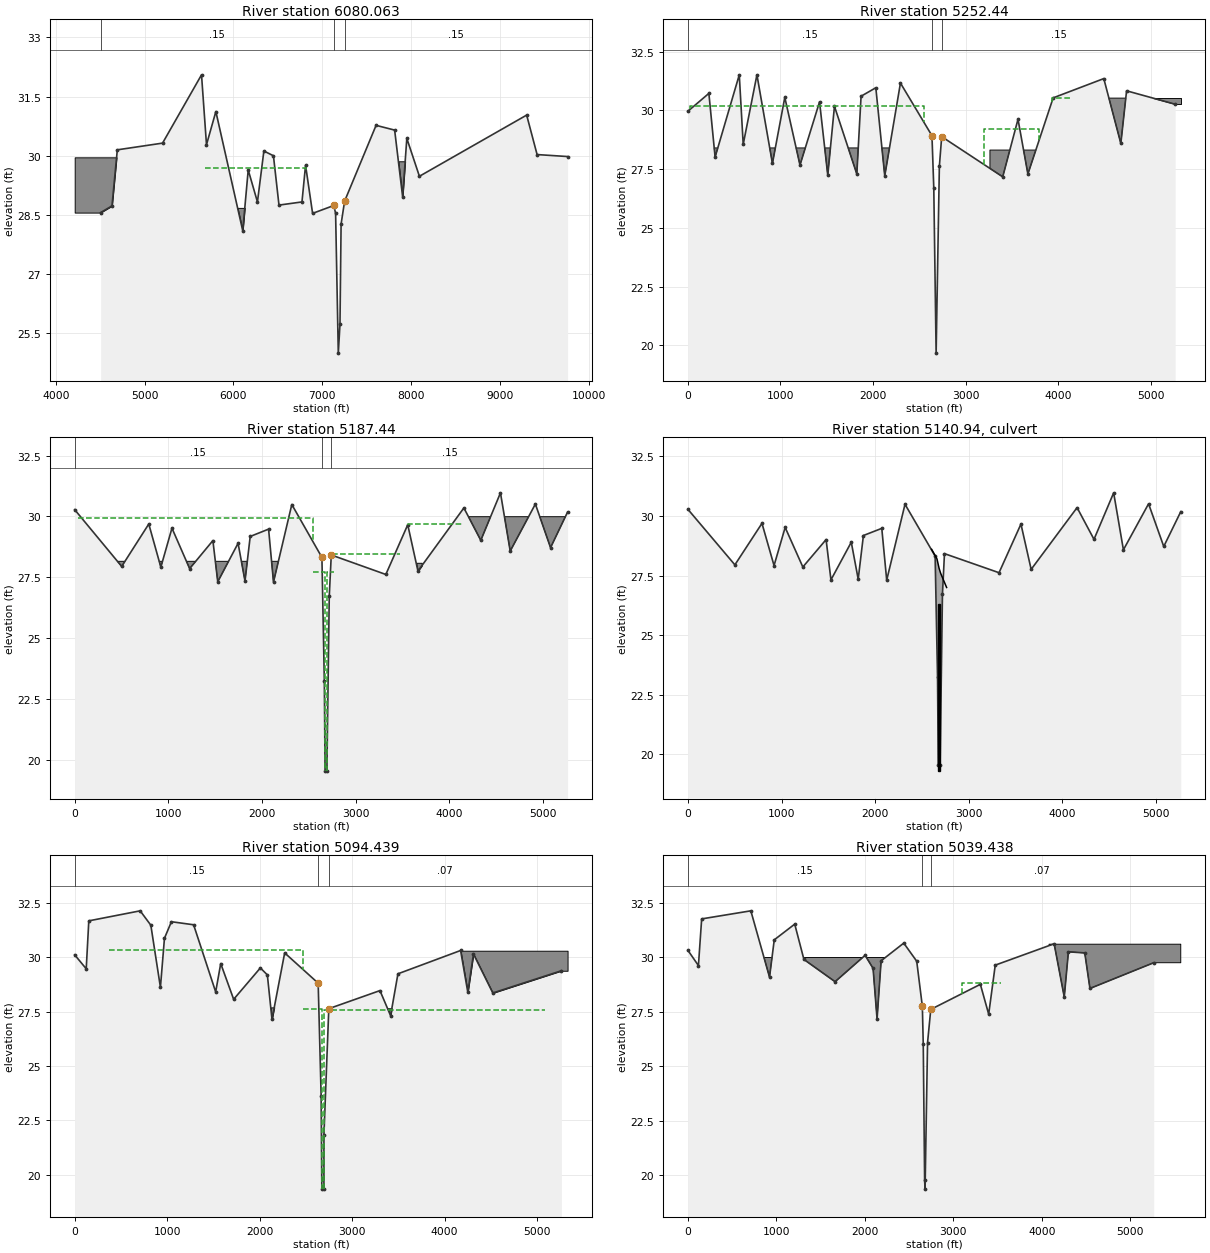
Type RM Length L Ch R = 1 ,6080.063,827.62,827.62,827.62
XS GIS Cut Line= 4
     3205605.369    13819921.191     3203391.943    13819817.951
     3202425.917    13819772.894     3200351.921    13819676.158
#Sta/Elev= 30
 4503.84   28.56 4631.85   28.73 4691.72   30.15 5201.37   30.32 5640.18   32.05
 5696.14   30.28 5801.67   31.12 6104.52    28.1 6166.02   29.64 6270.03   28.83
 6342.39   30.12 6450.13      30 6512.56   28.75 6771.49   28.83 6811.91   29.76
 6891.25   28.54 7130.06   28.74 7150.35   28.54 7180.64      25 7199.64   25.73
 7212.14   28.27 7251.87   28.85 7606.17   30.77 7815.31   30.65 7905.37   28.96
 7952.44   30.44  8094.2   29.48 9302.15   31.03 9419.72   30.03    9763   29.98
#Mann= 3 , 0 , 0
 4503.84     .15       0 7130.06    .015       0 7251.87     .15       0
#XS Ineff= 1 ,-1
 5679.18 6819.11   29.68
Permanent Ineff=
       F
#Block Obstruct= 3 ,-1
  4211.6 4703.07   29.96 5508.53 6191.13   28.68 7583.62 7965.87   29.86
Bank Sta=7130.06,7251.87
XS Rating Curve= 0
Exp/Cntr=.3,.1

Type RM Length L Ch R = 1 ,5252.44 ,65,65,65
XS GIS Cut Line= 4
     3205651.278     13819094.82       3203430.8    13818991.251
     3202464.774    13818946.194     3200393.747    13818849.596
#Sta/Elev= 30
       0   29.96  226.73   30.72   294.1   28.01  555.11   31.51  597.59   28.55
  745.87   31.51  913.31   27.74 1046.92   30.55 1210.91   27.67 1422.22   30.36
 1511.04   27.24 1583.36   30.17 1824.86   27.29 1870.81    30.6 2030.07   30.96
 2126.68   27.21  2296.1   31.16 2636.64   28.92  2656.3   26.69 2681.52   19.67
 2716.54   27.62 2741.75   28.88 3400.96   27.17 3566.02   29.62 3672.77   27.29
 3945.74   30.53 4492.66   31.35 4676.79   28.59 4738.92   30.83 5263.24   30.26
#Mann= 3 , 0 , 0
       0     .15       0 2636.64    .015       0 2741.75     .15       0
#XS Ineff= 3 ,-1
 3931.74 4143.34   30.52    27.3 2546.08   30.17 3201.37 3795.22   29.19
Permanent Ineff=
       F       F       F
#Block Obstruct= 3 ,-1
  163.82 2218.43    28.4  3262.8 3795.22   28.31  4184.3 5324.23   30.52
Bank Sta=2636.64,2741.75
XS Rating Curve= 0
Exp/Cntr=.5,.3

Type RM Length L Ch R = 1 ,5187.44 ,93,93,93
XS GIS Cut Line= 4
     3205654.884    13819029.917     3203433.829    13818926.322
     3202467.803    13818881.264     3200397.032    13818784.679
#Sta/Elev= 30
       0   30.28  501.96   27.95  791.21   29.69  920.13   27.92 1038.79   29.52
 1227.67   27.86 1475.99   29.01  1527.8   27.32 1744.93    28.9 1818.82   27.35
 1874.42   29.18 2070.65   29.48 2123.18   27.31 2318.66   30.49 2640.25   28.32
 2666.03   23.23 2673.81   19.55 2693.25   19.55 2718.54   26.72 2740.11   28.42
 3322.79   27.62 3556.81   29.66  3665.8   27.76 4156.27   30.35 4336.94   29.02
 4546.89   30.97 4651.01   28.58 4919.73   30.51 5081.81   28.72 5263.57   30.18
#Mann= 3 , 0 , 0
       0     .15       0 2640.25    .015       0 2740.11     .15       0
#XS Ineff= 6 ,-1
   34.13 2546.08   29.93 2546.08 2674.64   27.72 2693.24 2764.51   27.73
 2764.51  3474.4   28.46  3474.4 3556.31   27.73 3556.31 4143.34    29.7
Permanent Ineff=
       F       F       F       F       F       F
#Block Obstruct= 3 ,-1
  143.34 2232.08   28.16 3590.44 3706.48    28.1 4177.47 5351.54   29.99
Bank Sta=2640.25,2740.11
XS Rating Curve= 0
Exp/Cntr=.5,.3

Type RM Length L Ch R = 2 ,5140.94 ,,,
Node Photo=G:\C2001-041_Harris_County_FEMA\1-Armand_Bayou\Willow_Springs_TribB\Survey info\B112-04-S2P8.JPG
BEGIN DESCRIPTION:
San Augustine
END DESCRIPTION:
Bridge Culvert--1,0,-1,-1, 0
Deck Dist Width WeirC Skew NumUp NumDn MinLoCord MaxHiCord MaxSubmerge Is_Ogee
5,80,2.6,0, 5, 5, , , .95, 0, 0,0,,
    2603    2660    2683    2699    2763
    28.6    28.2    27.8    27.6      27
                                        
    2603    2660    2683    2699    2763
    28.6    28.2    27.8    27.6      27
                                        
BR Coef=-1 , 0 , 0 ,, 0 ,,,.8,-1,,0,
WSPro=,,,, 1 ,,,, 0 ,,,, 0 ,,,,-1 ,-1 ,-1 , 0 , 0 , 0 , 0 , 0
Multiple Barrel Culv=2,7,7,80,.012,.5,1,10,1,19.3,19.2, 2,Culvert #1  , 0 ,5
  2679.2  2680.2  2686.8  2687.8
Culvert Bottom n=.012
BC Design=,, 0 ,, 0 ,,,,,,

Type RM Length L Ch R = 1 ,5094.439,55,55,55
XS GIS Cut Line= 4
     3205660.043    13818937.057     3203438.162    13818833.423
     3202472.136    13818788.365     3200401.732    13818691.797
#Sta/Elev= 30
       0    30.1  124.86   29.46  152.71   31.66  708.31   32.12  823.65   31.46
  927.32   28.61  970.93   30.86 1046.06   31.62 1286.25   31.48 1524.95    28.4
 1579.58    29.7 1719.41   28.06 2008.39    29.5 2083.83   29.18 2134.01   27.14
 2271.28   30.19 2633.55    28.8 2665.62   23.64 2673.08   19.35 2695.63   19.35
  2695.8   21.84 2748.53   27.63 3301.84   28.46 3416.62   27.31 3496.33   29.23
 4174.06    30.3 4252.16   28.38 4313.18   30.14 4522.45   28.35 5264.03   29.37
#Mann= 3 , 0 , 0
       0     .15       0 2633.55    .015       0 2748.53     .07       0
#XS Ineff= 3 ,-1
   368.6 2470.99   30.32 2470.99 2675.02    27.6 2694.37 5092.15   27.58
Permanent Ineff=
       F       F       F
#Block Obstruct= 3 ,-1
 1255.97 2450.51   27.69  3290.1 3488.05   27.65 4177.47 5331.06   30.29
Bank Sta=2633.55,2748.53
XS Rating Curve= 0
Exp/Cntr=.5,.3

Type RM Length L Ch R = 1 ,5039.438,835.02,835.02,835.02
XS GIS Cut Line= 4
     3205663.094    13818882.139     3203440.724    13818778.483
     3202474.699    13818733.425     3200404.511    13818636.867
#Sta/Elev= 30
       0   30.31  119.16   29.61  155.76   31.75  711.37   32.12  922.55   29.08
  976.06   30.79 1207.38   31.51 1311.39   29.89 1663.55   28.87 2002.77   30.08
 2092.87   29.48 2137.92   27.16 2183.75   29.83 2439.59   30.64  2585.9   29.81
 2649.66   27.74 2659.88      26 2675.32   19.76 2680.41   19.36 2708.54   26.08
 2744.86    27.6 3305.27   28.75 3399.29   27.38 3473.43   29.63 4138.96   30.61
 4253.28   28.17 4300.26   30.24 4485.13   30.19 4543.61   28.56  5264.3   29.74
#Mann= 3 , 0 , 0
       0     .15       0 2649.66    .015       0 2744.86     .07       0
#XS Ineff= 1 ,-1
 3092.15 3542.66    28.8
Permanent Ineff=
       F
#Block Obstruct= 2 ,-1
  675.77 2464.16   29.98 4081.91 5569.97   30.59
Bank Sta=2649.66,2744.86
XS Rating Curve= 0
Exp/Cntr=.3,.1

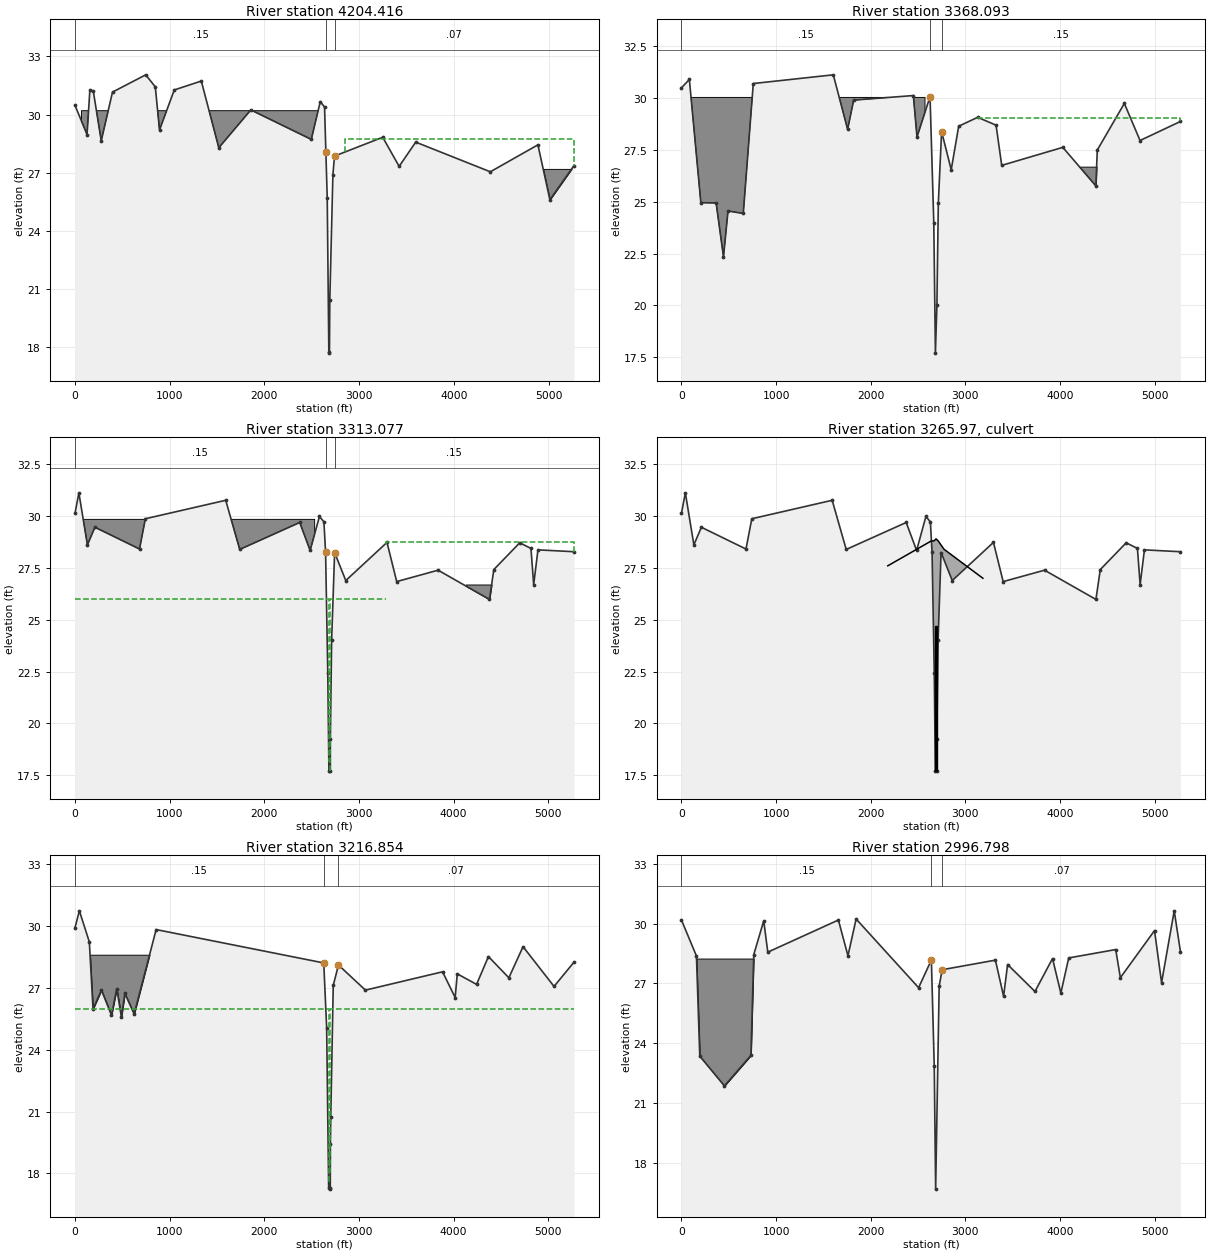
Type RM Length L Ch R = 1 ,4204.416,836.08,836.32,836.57
XS GIS Cut Line= 4
     3205709.413    13818048.392     3203479.629     13817944.39
     3202513.603    13817899.332     3200446.711    13817802.927
#Sta/Elev= 30
       0   30.48  127.05   28.97  157.08   31.26  192.84   31.22  277.21   28.65
  396.04   31.16  746.79   32.05  847.83   31.43  892.47   29.21 1048.22   31.27
 1333.67   31.73 1518.36   28.29 1856.45   30.24 2494.74   28.72 2589.73   30.67
 2634.77   30.39 2648.68   28.08 2663.08   25.71 2680.15    17.7 2686.55   17.78
  2690.3   20.44 2722.86   26.89 2739.89   27.86 3248.85   28.83 3422.41   27.33
 3597.39   28.58 4384.97   27.05 4887.42   28.44 5013.71   25.61 5268.42   27.37
#Mann= 3 , 0 , 0
       0     .15       0 2648.68    .015       0 2739.89     .07       0
#XS Ineff= 1 ,-1
 2853.24 5747.44   28.76
Permanent Ineff=
       F
#Block Obstruct= 2 ,-1
   68.26  2580.2    30.2 4880.55 5317.41    27.2
Bank Sta=2648.68,2739.89
XS Rating Curve= 0
Exp/Cntr=.3,.1

Type RM Length L Ch R = 1 ,3368.093,55.01,55.02,55.02
XS GIS Cut Line= 4
     3205755.439    13817219.927     3203569.659    13817112.589
     3202582.466    13817064.111     3200489.298    13816961.321
#Sta/Elev= 30
       0    30.5   83.52   30.91  204.94   24.96  366.15   24.95  444.12   22.35
  491.94   24.56  653.14   24.44  758.95   30.71 1604.37   31.13 1755.71    28.5
 1819.68   29.91 2450.33   30.13 2488.62   28.13 2626.57   30.08 2666.08      24
 2683.15    17.7  2699.1      20 2714.05   24.93 2748.71   28.39 2850.28   26.55
 2929.28   28.65 3129.94   29.08 3324.13    28.7 3383.91   26.76 4029.39   27.63
 4378.21   25.77 4393.71    27.5 4679.44   29.75 4845.32   27.96 5272.49   28.88
#Mann= 3 , 0 , 0
       0     .15       0 2626.57    .015       0 2748.71     .15       0
#XS Ineff= 1 ,-1
 3126.28  5447.1   29.03
Permanent Ineff=
       F
#Block Obstruct= 2 ,-1
   40.96 2573.38   30.04 4168.14 4632.74    26.7
Bank Sta=2626.57,2748.71
XS Rating Curve= 0
Exp/Cntr=.5,.3

Type RM Length L Ch R = 1 ,3313.077,96.22,96.22,96.22
XS GIS Cut Line= 4
      3205758.49     13817165.01     3203572.357    13817057.655
     3202585.163    13817009.177     3200492.077    13816906.392
#Sta/Elev= 30
       0   30.13   41.04   31.12  131.15   28.61   210.6   29.46  681.68   28.41
  743.46   29.87  1592.6   30.76 1740.84   28.39  2374.8   29.69 2484.62   28.34
 2583.03   29.98 2630.32   29.72 2647.99   28.25  2671.1   22.44 2683.09    17.7
 2698.25    17.7  2698.5   19.25  2711.7      24 2743.27   28.24 2861.27   26.89
  3296.7   28.73 3399.35   26.84 3836.61   27.39 4379.44   25.98 4425.64   27.42
 4699.31   28.71 4817.99   28.44  4846.7   26.69 4891.88   28.37 5272.76   28.28
#Mann= 3 , 0 , 0
       0     .15       0 2647.99    .015       0 2743.27     .15       0
#XS Ineff= 3 ,-1
       0 2681.94      26 2698.12 3283.28      26 3283.28 5272.76   28.73
Permanent Ineff=
       F       F       F
#Block Obstruct= 2 ,-1
   34.13 2532.42   29.84 4128.32 4526.55    26.7
Bank Sta=2647.99,2743.27
XS Rating Curve= 0
Exp/Cntr=.5,.3

Type RM Length L Ch R = 2 ,3265.97 ,,,
BEGIN DESCRIPTION:
P Street
END DESCRIPTION:
Bridge Culvert--1,0,-1,-1, 0
Deck Dist Width WeirC Skew NumUp NumDn MinLoCord MaxHiCord MaxSubmerge Is_Ogee
5,86,2.6,0, 7, 7, , , .95, 0, 0,0,,
    2180    2640    2668    2690    2713    2774    3185
    27.6    28.8    28.8    28.9    28.8    28.4      27
                                                        
    2180    2640    2668    2690    2713    2774    3185
    27.6    28.8    28.8    28.9    28.8    28.4      27
                                                        
BR Coef=-1 , 0 , 0 ,, 0 ,,,.8,-1,,0,
WSPro=,,,, 1 ,,,, 0 ,,,, 0 ,,,,-1 ,-1 ,-1 , 0 , 0 , 0 , 0 , 0
Multiple Barrel Culv=2,7,7,86,.013,.5,1,10,1,17.7,17.2, 2,Culvert #1  , 0 ,5
    2686    2686    2694    2694
Culvert Bottom n=.013
BC Design=,, 0 ,, 0 ,,,,,,

Type RM Length L Ch R = 1 ,3216.854,220.04,220.06,220.07
XS GIS Cut Line= 4
     3205763.815    13817069.156     3203577.066    13816961.771
     3202589.872    13816913.293     3200496.929    13816810.514
#Sta/Elev= 30
       0   29.93   46.37   30.75   151.5   29.24  190.39   25.98  279.59    26.9
  385.65   25.68  441.53   26.97  490.61   25.58  526.95   26.74  625.07   25.74
  857.59   29.84 2628.72   28.22 2659.52   25.07  2680.6    17.3 2689.77   17.24
 2697.63    17.3  2699.1   19.44  2702.9   20.74 2729.05   27.13  2784.5   28.12
 3069.08    26.9 3884.07   27.79 4017.55   26.54 4039.77   27.69 4243.69   27.18
 4368.98   28.53  4584.8    27.5  4734.9   29.01 5062.41   27.08 5273.23   28.26
#Mann= 3 , 0 , 0
       0     .15       0 2628.72    .015       0  2784.5     .07       0
#XS Ineff= 2 , 0
       0 2680.06      26 2698.13       0      26
Permanent Ineff=
       F       F
#Block Obstruct= 1 ,-1
   61.43 1071.67   28.62
Bank Sta=2628.72,2784.5
XS Rating Curve= 0
Exp/Cntr=.5,.3

Type RM Length L Ch R = 1 ,2996.798,628.01,628.01,628.01
XS GIS Cut Line= 4
     3205776.019     13816849.49     3203587.856    13816742.036
     3202600.662    13816693.558     3200508.047    13816590.795
#Sta/Elev= 30
       0   30.18  158.32   28.38  193.75   23.36  454.03   21.87   734.4    23.4
  764.44   28.45  869.76   30.14   912.4   28.57 1658.64   30.18 1759.83   28.39
 1846.19   30.23 2506.54   26.79  2641.7   28.18 2671.73   22.88 2686.75    16.7
 2723.89   26.87 2755.78   27.69 3318.37   28.17 3404.76   26.36 3447.15   27.95
 3736.45    26.6 3921.96   28.25 4010.06   26.52 4093.14   28.28 4589.91    28.7
  4639.1   27.29 5000.06   29.65 5074.63   27.04  5208.3   30.64 5274.32   28.59
#Mann= 3 , 0 , 0
       0     .15       0  2641.7    .015       0 2755.78     .07       0
#Block Obstruct= 1 ,-1
   47.78  982.94   28.25
Bank Sta=2641.7,2755.78
XS Rating Curve= 0
Exp/Cntr=.3,.1

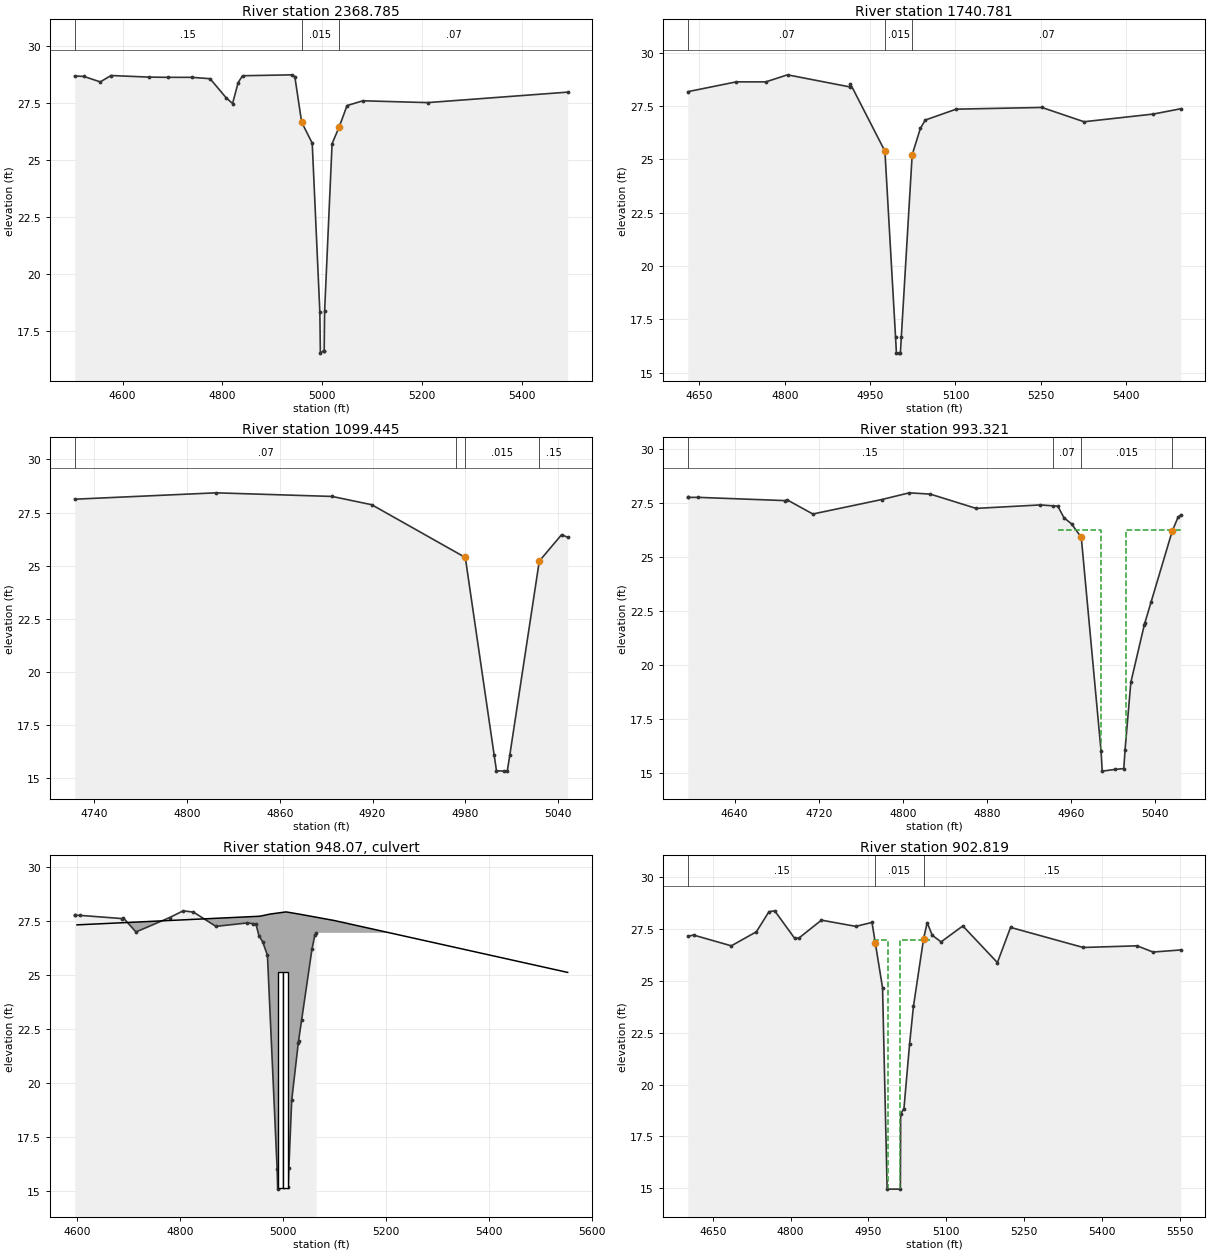
Type RM Length L Ch R = 1 ,2368.785,628,628,628
XS GIS Cut Line= 2
     3203618.658    13816114.792     3202631.465    13816066.313
#Sta/Elev= 27
 4503.84   28.68 4522.11   28.66 4555.12   28.42 4576.69    28.7 4653.15   28.63
 4691.41   28.62 4738.43   28.62 4775.32   28.56 4807.17   27.73 4820.38   27.47
 4831.61   28.39 4840.32   28.69 4940.52   28.73 4945.21   28.65  4958.9   26.65
 4980.08   25.73 4995.38   18.32 4996.45   16.51 5002.85   16.61 5004.08   16.61
  5004.9   18.34 5019.92   25.71 5034.32   26.45 5049.87   27.38 5081.82   27.59
 5211.48   27.51 5492.22   27.97
#Mann= 3 , 0 , 0
 4503.84     .15       0  4958.9    .015       0 5034.32     .07       0
Bank Sta=4958.9,5034.32
XS Rating Curve= 0
Exp/Cntr=.3,.1

Type RM Length L Ch R = 1 ,1740.781,457.39,641.34,815.09
XS GIS Cut Line= 2
     3203527.641    13815481.565     3202662.267    13815439.069
#Sta/Elev= 20
 4629.61   28.18 4714.73   28.64 4766.66   28.64  4804.9   28.97 4914.99    28.4
 4915.52   28.54 4976.05   25.39  4994.7   16.69 4996.24   15.94  5001.1   15.92
 5003.25   15.93 5004.85   16.67 5023.95   25.22 5038.37   26.46    5047   26.85
 5101.35   27.36 5251.95   27.44 5326.02   26.77 5447.61   27.13 5496.03   27.38
#Mann= 3 , 0 , 0
 4629.61     .07       0 4976.05    .015       0 5023.95     .07       0
Bank Sta=4976.05,5023.95
XS Rating Curve= 0
Exp/Cntr=.3,.1

Type RM Length L Ch R = 1 ,1099.445,264.3,106.12,60.01
XS GIS Cut Line= 2
     3203538.783    13815479.832     3203557.632    13815159.856
#Sta/Elev= 13
 4727.23   28.13 4818.67   28.43 4893.82   28.26 4919.52   27.87 4980.05   25.39
  4998.7   16.11 5000.24   15.36  5005.1   15.34 5007.25   15.35 5008.85   16.09
 5027.95   25.22 5042.37   26.46  5046.3   26.34
#Mann= 4 ,-1 , 0
 4727.23     .07       0 4974.04     .15       0 4980.05    .015       0
 5027.95     .15       0
Bank Sta=4980.05,5027.95
XS Rating Curve= 0
Exp/Cntr=.5,.3

Type RM Length L Ch R = 1 ,993.321 ,90.52,90.5,60.01
XS GIS Cut Line= 3
     3204041.119    13815210.981     3203607.848     13815179.44
     3203581.202    13815157.289
#Sta/Elev= 28
 4595.43   27.74  4595.7   27.74 4605.57   27.74 4688.13   27.59  4690.1   27.62
 4714.42   26.97 4780.01   27.64 4806.19   27.95 4826.21   27.89 4869.77   27.23
  4930.8   27.39 4942.54   27.35 4947.56   27.33 4953.32    26.8 4960.63   26.51
 4969.83   25.89 4988.67   15.99 4989.75   15.07 5002.17   15.15 5010.32   15.19
 5011.45   16.04    5017   19.18 5029.85   21.85 5030.26   21.92 5036.35   22.91
 5056.31   26.17 5061.92   26.82  5064.5   26.93
#Mann= 4 ,-1 , 0
 4595.43     .15       0 4942.54     .07       0 4969.83    .015       0
 5056.31     .15       0
#XS Ineff= 2 ,-1
 4947.35  4988.5   26.24 5012.32  5064.5   26.24
Permanent Ineff=
       F       F
Bank Sta=4969.83,5056.31
XS Rating Curve= 0
Exp/Cntr=.5,.3

Type RM Length L Ch R = 2 ,948.07  ,,,
BEGIN DESCRIPTION:
Pasadena Boulevard
END DESCRIPTION:
Bridge Culvert--1,0,-1,-1, 0
Deck Dist Width WeirC Skew NumUp NumDn MinLoCord MaxHiCord MaxSubmerge Is_Ogee
7,80,2.6,0, 7, 7, , , .95, 0, 0,0,,
    4600    4955    4975    5006    5031    5100    5553
    27.3    27.7    27.8    27.9    27.8    27.5    25.1
                                                        
    4600    4955    4975    5006    5031    5100    5553
    27.3    27.7    27.8    27.9    27.8    27.5    25.1
                                                        
BR Coef=-1 , 0 , 0 ,, 0 ,,,.8,-1,,0,
WSPro=,,,, 1 ,,,, 0 ,,,, 0 ,,,,-1 ,-1 ,-1 , 0 , 0 , 0 , 0 , 0
Multiple Barrel Culv=2,10,10,80,.013,.5,1,10,1,15.1,14.9, 2,Culvert #1  , 0 ,7
  4994.7  4994.7  5005.3  5005.3
Culvert Bottom n=.013
BC Design=,, 0 ,, 0 ,,,,,,

Type RM Length L Ch R = 1 ,902.819 ,60.01,60.01,60.01
XS GIS Cut Line= 3
     3204047.653    13815121.218     3203215.433    13815060.635
     3203099.996    13815052.232
#Sta/Elev= 30
 4601.89   27.16 4612.91   27.22 4685.77    26.7 4734.16   27.38 4758.34   28.35
 4769.42   28.39 4807.59   27.07  4815.8   27.07  4859.4   27.94 4925.63   27.64
 4956.95   27.83  4963.2   26.85 4977.26   24.67  4986.1   14.95 5011.65   14.95
  5012.2   18.58  5018.5   18.84 5029.33   21.95 5036.76   23.77 5056.33   27.04
 5063.26   27.82 5073.04   27.21 5090.06   26.89 5131.98   27.66 5198.62   25.89
 5223.97   27.59 5364.05   26.62 5467.87    26.7 5498.55    26.4 5552.05    26.5
#Mann= 3 , 0 , 0
 4601.89     .15       0  4963.2    .015       0 5056.33     .15       0
#XS Ineff= 2 ,-1
 4958.62 4988.69   26.99 5011.32 5067.79   26.99
Permanent Ineff=
       F       F
Bank Sta=4963.2,5056.33
XS Rating Curve= 0
Exp/Cntr=.5,.3

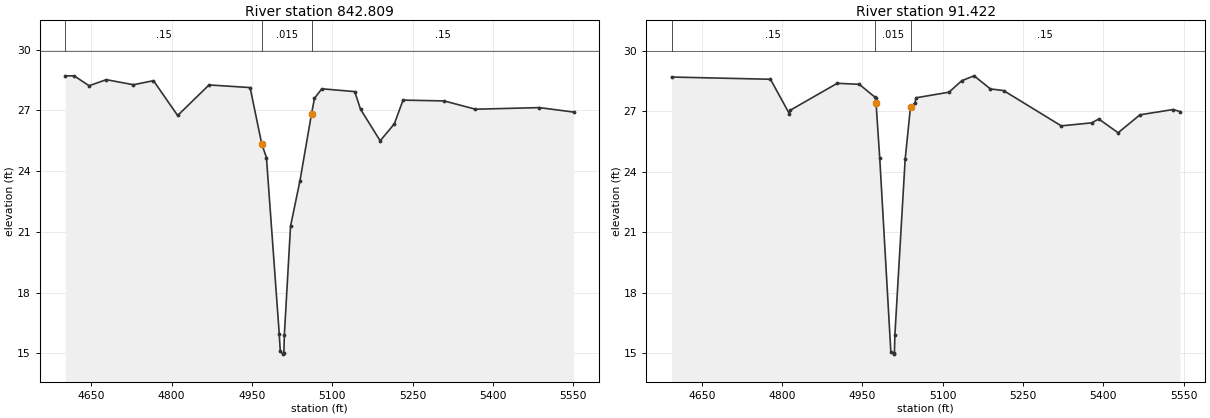
Type RM Length L Ch R = 1 ,842.809 ,751.39,751.39,751.39
XS GIS Cut Line= 3
     3204052.009    13815061.376     3203219.789    13815000.793
     3203104.798    13814992.422
#Sta/Elev= 30
 4601.12   28.71 4617.76   28.71 4645.75   28.22 4677.87   28.52 4728.53   28.27
 4766.06   28.47 4811.18   26.75 4869.88   28.26 4946.54   28.13  4968.2   25.36
  4977.1   24.67 5000.98   15.97 5002.97   15.09  5008.3   14.96 5009.65   15.01
 5010.55   15.91  5022.1   21.28 5039.75   23.53 5061.38   26.84 5066.86    27.6
 5080.54   28.07 5142.06   27.93 5152.87   27.06 5189.61    25.5  5216.1   26.34
 5232.29   27.51 5309.04   27.47 5367.65   27.06 5486.82   27.14 5550.84   26.92
#Mann= 3 , 0 , 0
 4601.12     .15       0  4968.2    .015       0 5061.38     .15       0
Bank Sta=4968.2,5061.38
XS Rating Curve= 0
Exp/Cntr=.3,.1

Type RM Length L Ch R = 1 ,91.422  ,92.96,116.91,89.88
XS GIS Cut Line= 2
     3204102.618    13814311.854     3203155.407      13814242.9
#Sta/Elev= 30
 4593.52   28.69 4778.11   28.58 4813.41   26.87 4815.41   27.05 4902.88   28.38
 4944.02   28.33 4973.41   27.69 4974.64   27.66  4975.3   27.42 4982.26   24.67
 5002.97   15.09  5008.3   14.96 5009.65   15.01 5010.55   15.91 5029.74   24.61
 5039.75   27.22 5048.25   27.41 5049.84   27.66 5111.73   27.94 5135.55   28.51
 5158.46   28.75  5189.1    28.1 5213.62   28.02 5321.46   26.27  5378.1   26.42
 5391.49   26.61  5427.6   25.93 5468.62   26.82 5530.45   27.08 5543.24   26.98
#Mann= 3 ,-1 , 0
 4593.52     .15       0 4973.41    .015       0 5039.75     .15       0
Bank Sta=4975.3,5039.75
XS Rating Curve= 0
Exp/Cntr=.3,.1

Chan Stop Cuts=-1

--- B112_04_00.g03 (geometry) ---

Geom Title=B112-04-00 June 2007 (Floodway)
Version=Version 3.0.1  Mar 2001

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
River Reach=B112-04-00      ,B112-04-00_0001